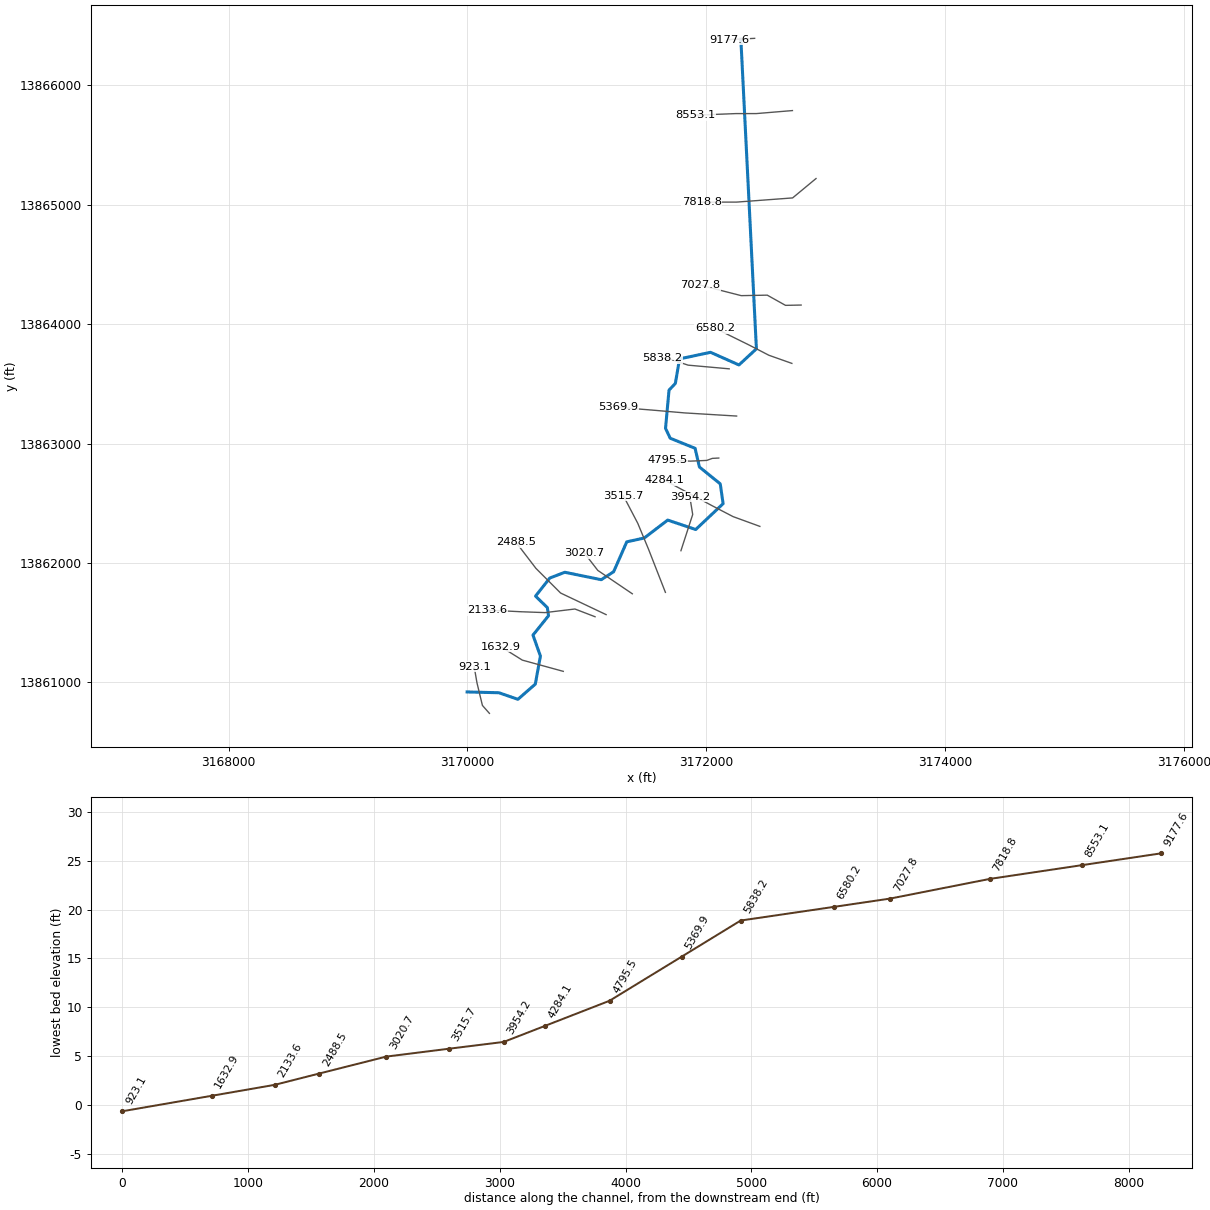
--- P109-00-00.PRJ (project) ---

Proj Title=P109-00-00
Current Plan=p02
Default Exp/Contr=.3,.1
English Units
Geom File=g01
Flow File=f01
Flow File=f02
Plan File=p01
Plan File=p02
Y Axis Title=Elevation
X Axis Title(PF)=Main Channel Distance
X Axis Title(XS)=Station
BEGIN DESCRIPTION:
Greens Bayou Watershed
Sulphur Gully
HCFCD Unit P109-00-00
Flood Hazard Model
10, 2, 1, 0.2% Event
Filename P109-00-00.prj
Prepared by:  Watershed Concepts  Date:
Reviewed by:                      Date:
STATUS FINAL
END DESCRIPTION:
DSS Export Rating Curves= 0
DSS Export Rating Curve Sorted= 0
DSS Export Volume Flow Curves= 0
DXF OffsetX= 0
DXF OffsetY= 0
DXF ScaleX= 1
DXF ScaleY= 10

--- P109-00-00.p02 (plan) ---

Plan Title=Floodway
Version=Version 3.0.1  Mar 2001
Short Identifier=Floodway0607
Geom File=g01
Flow File=f02
Subcritical Flow
K Sum by GR= 0
Std Step Tol= 0.01
Critical Tol= 0.01
Num of Std Step Trials= 20
Max Error Tol= 0.3
Flow Tol Ratio= 0.001
Split Flow NTrial= 30
Split Flow Tol= 0.02
Split Flow Ratio= 0.02
Log Output Level= 0
Friction Slope Method= 1
Unsteady Friction Slope Method= 2
Parabolic Critical Depth
Global Vel Dist= 0 , 0 , 0
Global Log Level= 0
CheckData=True
Encroach Param=-1 ,0,0, 2
Encroach River=P109-00-00
Encroach Reach=Reach - 1
Encroach Node=9177.6
       1  4985.4    5020
Encroach Node=8553.1
       1  4981.1  5014.9
Encroach Node=7818.8
       1 4983.05  5014.9
Encroach Node=7027.8
       1  4979.4  5027.9
Encroach Node=6580.2
       1  4993.5    5055
Encroach Node=5838.2
       1    4970    5050
Encroach Node=5369.9
       1    4950    5030
Encroach Node=4795.5
       1    4992    5017
Encroach Node=4284.1
       1    4965    5035
Encroach Node=3954.2
       1  4988.8  5062.5
Encroach Node=3515.7
       1    4965    5035
Encroach Node=3020.7
       1    4930    5020
Encroach Node=2488.5
       1    4963    5050
Encroach Node=2133.6
       1    4965    5055
Encroach Node=1632.9
       1    4970    5025
Encroach Node=923.1
       1    4960    5028
Encroach Reach=P109-00-00_0009
Encroach Node=9177.6
       1  4985.4    5020
Encroach Node=8553.1
       1  4981.1  5014.9
Encroach Node=7818.8
       1 4983.05  5014.9
Encroach Node=7027.8
       1  4979.4  5027.9
Encroach Node=6580.2
       1  4993.5    5055
Encroach Node=5838.2
       1    4970    5050
Encroach Node=5369.9
       1    4950    5030
Encroach Node=4795.5
       1    4992    5017
Encroach Node=4284.1
       1    4965    5035
Encroach Node=3954.2
       1  4988.8  5062.5
Encroach Node=3515.7
       1    4965    5035
Encroach Node=3020.7
       1    4930    5020
Encroach Node=2488.5
       1    4963    5050
Encroach Node=2133.6
       1    4965    5055
Encroach Node=1632.9
       1    4970    5025
Encroach Node=923.1
       1    4960    5028
Computation Interval=1HOUR
Output Interval=1HOUR
Run HTab= 0
Run UNet= 0
Run PostProcess= 0
UNET Theta= 1
UNET ZTol= 0.02
UNET ZSATol= 0.1
UNET MxIter= 20
UNET MaxInSteps= 20
UNET DtIC= 0
UNET DtMin= 0
UNET MaxCRTS= 20
UNET WFStab= 2
UNET SFStab= 1
UNET WFX= 1
UNET SFX= 1
UNET Convert EG Bridges=-1
UNET Use Existing IB Tables=-1
Instantaneous Interval=1HOUR
Write IC File= 0
Write Velocity= 0
Write Detailed= 0

--- P109-00-00.p01 (plan) ---

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Plan Title=FEMA Effective June 2007
Short Identifier=FEMAeff0607
Geom File= g01
Flow File= f01
Interactive Comp Mode
Encroach Param= -1, 0, 0, 0

--- P109-00-00.f02 (steady flow) ---

Flow Title= Floodway
Number of Profiles= 2
Profile Names=1PCT_100yr, 1PCTFloodway_100yrFW
River Rch & RM=P109-00-00,P109-00-00_0009,9177.6
     482     482
River Rch & RM=P109-00-00,P109-00-00_0009,8553.1
     528     528
River Rch & RM=P109-00-00,P109-00-00_0009,7818.8
     584     584
River Rch & RM=P109-00-00,P109-00-00_0009,7027.8
     617     617
River Rch & RM=P109-00-00,P109-00-00_0009,6580.2
     678     678
River Rch & RM=P109-00-00,P109-00-00_0009,5838.2
     719     719
River Rch & RM=P109-00-00,P109-00-00_0009,5369.9
     773     773
River Rch & RM=P109-00-00,P109-00-00_0009,4795.5
     824     824
River Rch & RM=P109-00-00,P109-00-00_0009,4284.1
     859     859
River Rch & RM=P109-00-00,P109-00-00_0009,3954.2
     907     907
River Rch & RM=P109-00-00,P109-00-00_0009,3515.7
     965     965
River Rch & RM=P109-00-00,P109-00-00_0009,3020.7
    1032    1032
River Rch & RM=P109-00-00,P109-00-00_0009,2488.5
    1079    1079
River Rch & RM=P109-00-00,P109-00-00_0009,2133.6
    1149    1149
River Rch & RM=P109-00-00,P109-00-00_0009,1632.9
    1256    1256
Boundary for River Rch & Prof#=P109-00-00,P109-00-00_0009, 1
Up Type= 0
Dn Type= 3
Dn Slope= 0.00240
Boundary for River Rch & Prof#=P109-00-00,P109-00-00_0009, 2
Up Type= 0
Dn Type= 3
Dn Slope= 0.00240

--- P109-00-00.f01 (steady flow) ---

Flow Title= FEMA Effective June 2007
Number of Profiles= 4
Profile Names=10PCT_10yr, 2PCT_50yr, 1PCT_100yr, 0.2PCT_500yr
River Rch & RM=P109-00-00,P109-00-00_0009,9177.6
     285     416     482     669
River Rch & RM=P109-00-00,P109-00-00_0009,8553.1
     313     456     528     733
River Rch & RM=P109-00-00,P109-00-00_0009,7818.8
     346     503     584     810
River Rch & RM=P109-00-00,P109-00-00_0009,7027.8
     366     532     617     857
River Rch & RM=P109-00-00,P109-00-00_0009,6580.2
     401     584     678     941
River Rch & RM=P109-00-00,P109-00-00_0009,5838.2
     426     620     719     997
River Rch & RM=P109-00-00,P109-00-00_0009,5369.9
     457     666     773    1072
River Rch & RM=P109-00-00,P109-00-00_0009,4795.5
     488     710     824    1143
River Rch & RM=P109-00-00,P109-00-00_0009,4284.1
     508     740     859    1192
River Rch & RM=P109-00-00,P109-00-00_0009,3954.2
     537     782     907    1259
River Rch & RM=P109-00-00,P109-00-00_0009,3515.7
     572     832     965    1340
River Rch & RM=P109-00-00,P109-00-00_0009,3020.7
     611     890    1032    1432
River Rch & RM=P109-00-00,P109-00-00_0009,2488.5
     639     931    1079    1498
River Rch & RM=P109-00-00,P109-00-00_0009,2133.6
     680     991    1149    1595
River Rch & RM=P109-00-00,P109-00-00_0009,1632.9
     744    1083    1256    1743
Boundary for River Rch & Prof#=P109-00-00,P109-00-00_0009, 1
Up Type= 0
Dn Type= 3
Dn Slope= 0.00240
Boundary for River Rch & Prof#=P109-00-00,P109-00-00_0009, 2
Up Type= 0
Dn Type= 3
Dn Slope= 0.00240
Boundary for River Rch & Prof#=P109-00-00,P109-00-00_0009, 3
Up Type= 0
Dn Type= 3
Dn Slope= 0.00240
Boundary for River Rch & Prof#=P109-00-00,P109-00-00_0009, 4
Up Type= 0
Dn Type= 3
Dn Slope= 0.00240

--- P109-00-00.g01 (geometry) ---

Geom Title=P109-00-00 June 2007
Version=Version 3.0.1  Mar 2001

River Reach=P109-00-00      ,P109-00-00_0009
Reach XY= 30
      3172289.71     13866386.96      3172419.91     13863792.97
      3172273.53     13863658.18      3172035.83     13863763.99
      3171776.39     13863708.91      3171741.13     13863503.54
      3171688.22      13863447.1      3171658.83     13863127.17
      3171698.12     13863044.44      3171906.38     13862960.09
       3171942.6     13862803.71      3172117.27      13862662.2
      3172140.99     13862496.13      3171911.65     13862279.96
      3171677.03     13862359.05      3171480.72     13862208.81
      3171334.33     13862176.92      3171224.18     13861926.18
      3171120.29     13861859.73      3170815.45     13861921.83
      3170689.94     13861873.84        3170570.     13861722.15
       3170669.1     13861626.24      3170679.13     13861558.06
      3170548.77     13861395.71      3170611.09     13861220.34
      3170568.31     13860985.19      3170422.67     13860857.99
      3170263.53     13860912.95      3169997.14     13860919.72

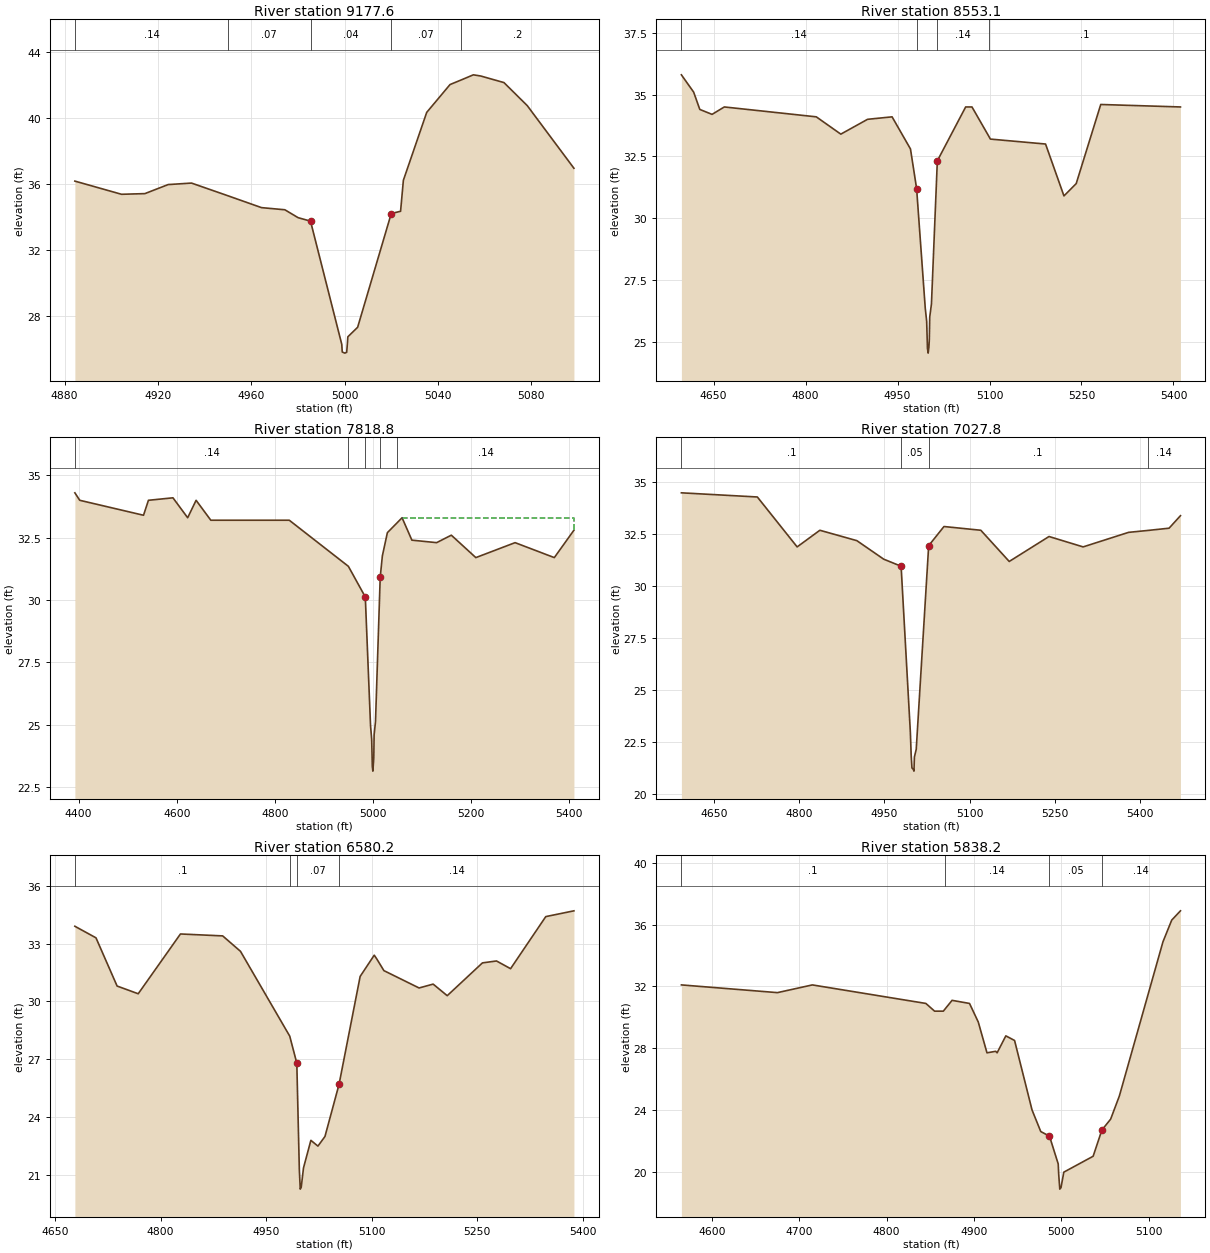
Type RM Length L Ch R = 1 ,9177.6  ,620.1,624.5,659.1
BEGIN DESCRIPTION:
Cross Section 9177.6
END DESCRIPTION:
XS GIS Cut Line= 5
      3172405.13     13866393.43      3172294.53     13866387.28
      3172284.52     13866386.73      3172231.47     13866386.78
      3172191.73     13866381.81
#Sta/Elev= 28
  4884.4   36.18  4904.4   35.38  4914.4   35.42  4924.4   35.97  4934.4   36.06
    4950   35.29  4964.4   34.57  4974.4   34.44  4980.1   33.96  4985.4   33.75
  4998.8   26.27    4999   25.81  5000.1   25.74  5000.9   25.79  5001.2   26.31
  5001.4   26.73  5005.6   27.31    5020   34.21    5024   34.35  5025.2   36.23
  5035.2   40.35  5045.2   42.04    5050   42.32  5055.2   42.63  5058.3   42.56
  5068.3   42.16  5078.3   40.76  5098.3   36.96
#Mann= 5 , 1 , 0
  4884.4     .14       0    4950     .07       0  4985.4     .04       0
    5020     .07       0    5050      .2       0
Bank Sta=4985.4,5020
XS Rating Curve= 0
Exp/Cntr=.3,.1

Type RM Length L Ch R = 1 ,8553.1  ,739,734.3,729.5
BEGIN DESCRIPTION:
Cross Section 8553.1-Interpolated
END DESCRIPTION:
XS GIS Cut Line= 4
      3172721.66     13865788.45      3172419.08     13865763.24
      3172248.77     13865763.24      3171909.07     13865749.92
#Sta/Elev= 29
  4597.5    35.8  4617.5    35.1  4627.5    34.4  4647.5    34.2  4667.5    34.5
  4817.5    34.1  4857.5    33.4  4901.1      34  4941.1    34.1  4971.1    32.8
  4981.1    31.2  4995.2   26.36  4997.5   25.83  4998.8   24.73  4999.9   24.54
  5001.1   24.77  5001.8   25.07  5002.5      26  5005.3   26.53  5014.9   32.32
  5061.1    34.5  5071.4    34.5  5098.7   33.32  5101.4    33.2  5191.4      33
  5221.4    30.9  5241.4    31.4  5281.4    34.6  5411.4    34.5
#Mann= 4 , 1 , 0
  4597.5     .14       0  4981.1     .05       0  5014.9     .14       0
  5098.7      .1       0
#XS Ineff= 2 , 0
       0                  5061.1       0    34.5
Permanent Ineff=
       F       F
Bank Sta=4981.1,5014.9
XS Rating Curve= 0
Exp/Cntr=.3,.1

Type RM Length L Ch R = 1 ,7818.8  ,973.9,791,772.9
BEGIN DESCRIPTION:
Cross Section 7818.8
END DESCRIPTION:
XS GIS Cut Line= 4
      3172919.18     13865219.26       3172723.1     13865056.98
      3172253.96     13865021.97      3171961.33     13865021.97
#Sta/Elev= 30
  4392.3    34.3  4402.3      34  4532.3    33.4  4542.3      34  4592.3    34.1
  4622.3    33.3  4639.5      34  4669.5    33.2  4829.5    33.2    4950   31.35
  4984.5   30.12  4995.2   24.95  4997.5   24.42  4998.8   23.32  4999.9   23.13
  5001.8   23.66  5002.5   24.59  5005.3   25.12  5014.9   30.91  5019.3   31.77
  5029.5    32.7    5050   33.11  5059.5    33.3  5079.5    32.4  5129.9    32.3
  5159.9    32.6  5209.9    31.7  5289.9    32.3  5369.9    31.7  5409.9    32.8
#Mann= 5 , 1 , 0
  4392.3     .14       0    4950     .07       0  4984.5     .04       0
  5014.9     .07       0    5050     .14       0
#XS Ineff= 2 , 0
       0                  5059.5       0    33.3
Permanent Ineff=
       F       F
Bank Sta=4984.5,5014.9
XS Rating Curve= 0
Exp/Cntr=.3,.1

Type RM Length L Ch R = 1 ,7027.8  ,527.7,447.6,340.7
BEGIN DESCRIPTION:
Cross Section 7027.8
END DESCRIPTION:
XS GIS Cut Line= 6
      3172794.58     13864159.82      3172663.58     13864157.23
      3172510.81     13864242.67       3172292.8     13864238.56
      3171971.95     13864320.83      3171950.27     13864327.03
#Sta/Elev= 24
  4592.9    34.5  4726.5    34.3  4796.5    31.9  4836.5    32.7  4901.6    32.2
  4948.8   31.31  4979.4   30.97  4995.7   22.97  4997.1   21.88  4998.5   21.27
  5000.8   21.21    5002   21.12  5002.8    21.8    5006   22.17  5027.9   31.96
  5054.8   32.88  5119.6    32.7  5169.6    31.2  5239.6    32.4  5299.6    31.9
  5379.6    32.6  5413.1   32.69  5450.8    32.8  5470.8    33.4
#Mann= 4 , 1 , 0
  4592.9      .1       0  4979.4     .05       0  5027.9      .1       0
  5413.1     .14       0
Bank Sta=4979.4,5027.9
XS Rating Curve= 0
Exp/Cntr=.3,.1

Type RM Length L Ch R = 1 ,6580.2  ,701.1,742,403.1
BEGIN DESCRIPTION:
Cross Section 6580.2-Interpolated
END DESCRIPTION:
XS GIS Cut Line= 4
       3172716.9     13863671.24      3172524.46     13863739.36
       3172352.4     13863828.16      3172073.22     13863965.73
#Sta/Elev= 30
  4678.2    33.9  4708.2    33.3  4738.2    30.8  4768.2    30.4  4828.2    33.5
  4888.2    33.4  4913.5    32.6  4983.5    28.2  4983.9   28.14  4993.5    26.8
  4997.1   21.27  4998.4   20.27  4999.8   20.37    5003   21.37  5013.5    22.8
  5023.5    22.5  5033.5      23  5053.5    25.7  5083.5    31.3  5103.5    32.4
  5107.2    32.2  5117.2    31.6  5167.2    30.7  5187.2    30.9  5207.2    30.3
  5257.2      32  5277.2    32.1  5297.2    31.7  5347.2    34.4  5387.2    34.7
#Mann= 4 , 1 , 0
  4678.2      .1       0  4983.9     .14       0  4993.5     .07       0
  5053.5     .14       0
Bank Sta=4993.5,5053.5
XS Rating Curve= 0
Exp/Cntr=.3,.1

Type RM Length L Ch R = 1 ,5838.2  ,483.7,468.3,465.9
BEGIN DESCRIPTION:
Cross Section 5838.2
END DESCRIPTION:
XS GIS Cut Line= 4
      3172192.15     13863625.63      3171847.97     13863656.45
      3171680.12     13863712.19      3171630.97     13863714.02
#Sta/Elev= 30
    4565    32.1    4675    31.6    4715    32.1    4845    30.9    4855    30.4
    4865    30.4    4867   30.54    4875    31.1    4895    30.9    4905    29.7
    4915    27.7    4925    27.8  4926.6    27.7  4936.6    28.8  4946.6    28.5
  4966.6      24  4976.6    22.6  4986.6    22.3  4996.6    20.5  4997.1   19.87
  4998.4   18.87  4999.8   18.97    5003   19.97  5036.6      21  5046.6    22.7
  5056.6    23.4  5066.6    24.9  5116.6    34.9  5126.6    36.3  5136.6    36.9
#Mann= 4 , 1 , 0
    4565      .1       0    4867     .14       0  4986.6     .05       0
  5046.6     .14       0
Bank Sta=4986.6,5046.6
XS Rating Curve= 0
Exp/Cntr=.3,.1

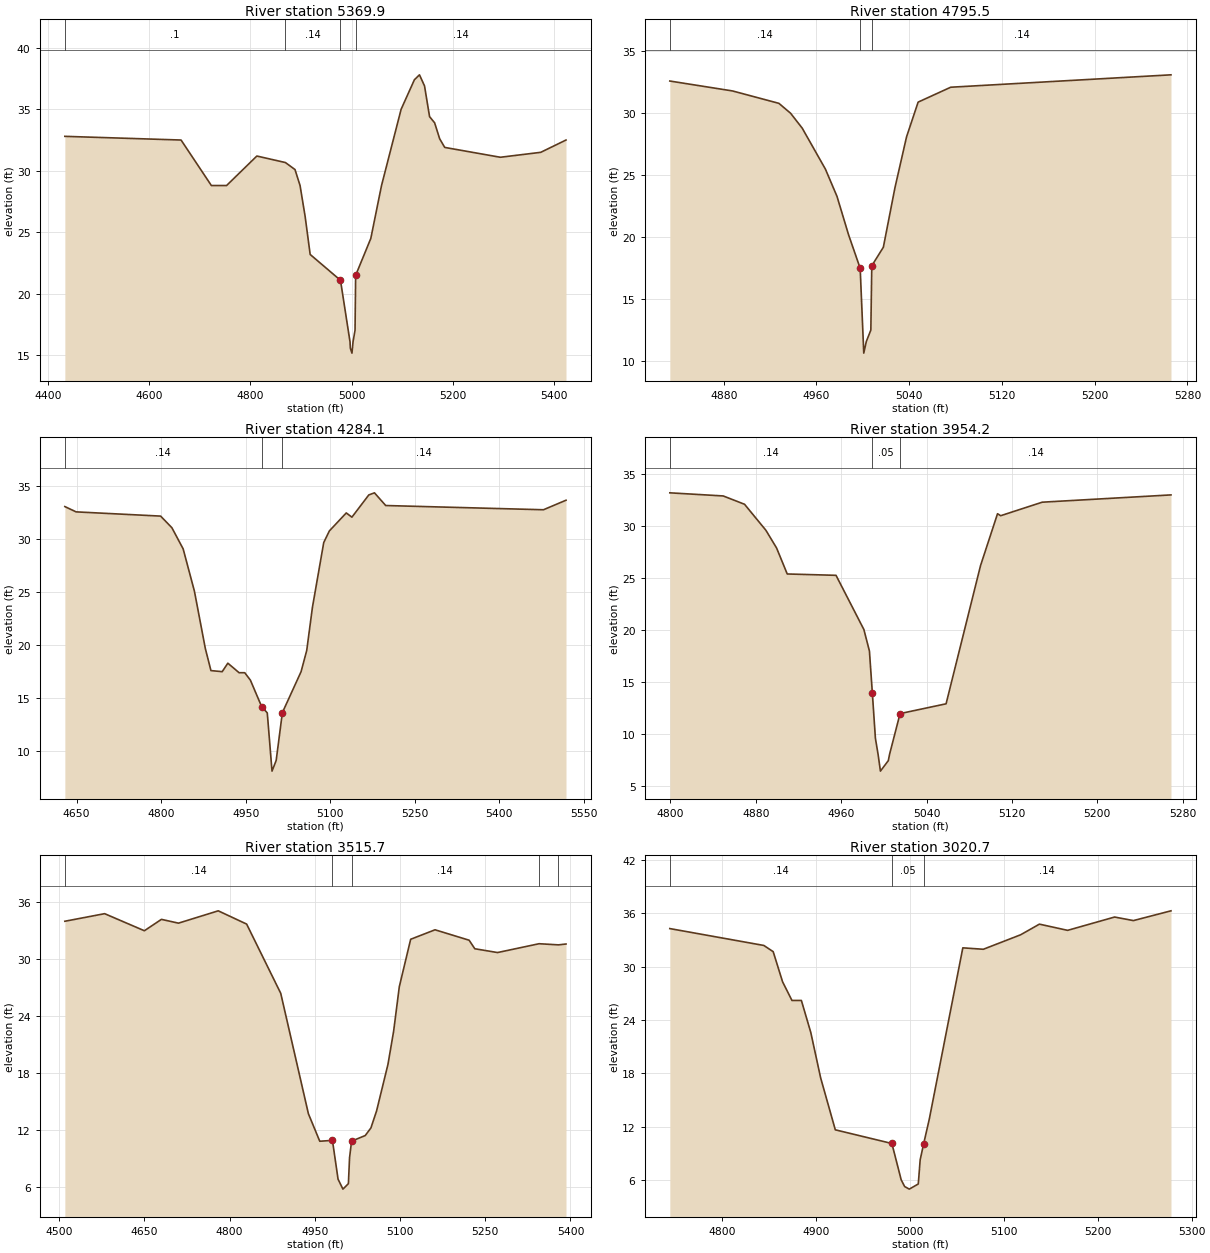
Type RM Length L Ch R = 1 ,5369.9  ,567.4,574.4,570.8
BEGIN DESCRIPTION:
Cross Section 5369.9-Interpolated
END DESCRIPTION:
XS GIS Cut Line= 4
      3172254.33     13863230.18      3171819.56     13863256.47
      3171564.24     13863278.67      3171265.26     13863302.85
#Sta/Elev= 30
  4432.6    32.8  4662.6    32.5  4722.6    28.8  4752.6    28.8  4812.6    31.2
  4869.1   30.67  4888.1    30.1  4898.1    28.8  4908.1    26.3  4918.1    23.2
  4978.1    21.1    4997   16.09  4997.6   15.58  5000.8   15.18    5003   16.12
  5006.9   17.04  5008.1    21.5  5038.1    24.5  5059.3    28.8  5098.1      35
  5124.4    37.4  5134.4    37.8  5144.4    36.9  5154.4    34.4  5164.4    33.9
  5174.4    32.6  5184.4    31.9  5294.4    31.1  5374.4    31.5  5424.4    32.5
#Mann= 4 , 1 , 0
  4432.6      .1       0  4869.1     .14       0  4978.1     .07       0
  5008.1     .14       0
Bank Sta=4978.1,5008.1
XS Rating Curve= 0
Exp/Cntr=.3,.1

Type RM Length L Ch R = 1 ,4795.5  ,533.4,511.4,434.2
BEGIN DESCRIPTION:
Cross Section 4795.5
END DESCRIPTION:
XS GIS Cut Line= 5
       3172104.9     13862878.54       3172050.9     13862875.86
      3172003.85      13862858.6      3171865.84      13862852.6
      3171676.08     13862861.66
#Sta/Elev= 19
  4833.5    32.6  4887.6    31.8  4927.6    30.8  4937.7      30  4947.7    28.8
  4967.7    25.5  4977.7    23.3  4987.7    20.2  4997.7    17.5  5000.8   10.66
    5003    11.6  5006.9   12.52  5007.7    17.7  5017.7    19.2  5027.7      24
  5037.7    28.1  5047.7    30.9  5075.8    32.1  5265.8    33.1
#Mann= 3 , 1 , 0
  4833.5     .14       0  4997.7     .05       0  5007.7     .14       0
Bank Sta=4997.7,5007.7
XS Rating Curve= 0
Exp/Cntr=.3,.1

Type RM Length L Ch R = 1 ,4284.1  ,367.5,329.9,212.9
BEGIN DESCRIPTION:
Cross Section 4284.1-Interpolated
END DESCRIPTION:
XS GIS Cut Line= 4
      3172448.86     13862306.19      3172224.04     13862388.24
      3172046.54     13862480.69      3171649.88     13862693.28
#Sta/Elev= 30
  4629.1    33.1  4649.1    32.6  4799.1    32.2  4819.1    31.1  4839.1    29.1
  4859.1    25.1  4878.4    19.7  4888.4    17.6  4908.4    17.5  4918.4    18.3
  4938.4    17.4  4948.4    17.4  4958.4    16.7  4978.4    14.2  4988.4    13.6
  4996.8     8.1  5004.2    9.11  5015.2   13.63  5048.4    17.5  5058.4    19.5
  5068.6    23.6  5088.6    29.7  5098.6    30.8  5128.6    32.5  5138.6    32.1
  5168.6    34.2  5178.6    34.4  5198.6    33.2  5478.6    32.8  5518.6    33.7
#Mann= 3 , 1 , 0
  4629.1     .14       0  4978.4     .05       0  5015.2     .14       0
Bank Sta=4978.4,5015.2
XS Rating Curve= 0
Exp/Cntr=.3,.1

Type RM Length L Ch R = 1 ,3954.2  ,392.4,438.5,495.6
BEGIN DESCRIPTION:
Cross Section 3954.2
END DESCRIPTION:
XS GIS Cut Line= 4
      3171787.84     13862102.54      3171787.84     13862102.55
       3171886.5     13862405.74      3171862.28     13862554.36
#Sta/Elev= 23
  4799.5    33.2  4849.5    32.9  4869.5    32.1  4889.5    29.6  4899.5    27.9
  4909.5    25.4  4955.2   25.27  4981.3   20.06  4986.5   17.99  4989.2      14
  4992.1     9.6  4994.7       8  4996.8    6.45  5004.2    7.46  5005.4    8.08
  5015.2   11.98  5058.3   12.92  5090.6   26.21  5106.5   31.19  5109.5      31
  5118.4    31.3  5148.4    32.3    5269      33
#Mann= 3 , 1 , 0
  4799.5     .14       0  4989.2     .05       0  5015.2     .14       0
Bank Sta=4989.2,5015.2
XS Rating Curve= 0
Exp/Cntr=.3,.1

Type RM Length L Ch R = 1 ,3515.7  ,426.9,495,475.9
BEGIN DESCRIPTION:
Cross Section 3515.7-Interpolated
END DESCRIPTION:
XS GIS Cut Line= 4
      3171657.85     13861753.64      3171516.19     13862115.66
        3171427.     13862330.77      3171306.33     13862561.62
#Sta/Elev= 30
    4510      34    4580    34.8    4650      33    4680    34.2    4710    33.8
    4780    35.1    4830    33.7    4890    26.4  4938.7    13.7  4958.7    10.8
    4981   10.89  4990.9     6.8  4999.5    5.75  5009.1    6.33  5011.1    9.05
  5014.7   10.81  5038.7    11.4  5048.7    12.2  5058.7      14  5078.7    18.9
  5088.7    22.4  5098.7    27.1  5118.7    32.1  5161.6    33.1  5221.6      32
  5231.6    31.1  5271.6    30.7  5344.7   31.63  5378.8   31.51  5392.1    31.6
#Mann= 5 , 1 , 0
    4510     .14       0    4981     .05       0  5014.7     .14       0
  5344.7      .1       0  5378.8      .2       0
Bank Sta=4981,5014.7
XS Rating Curve= 0
Exp/Cntr=.3,.1

Type RM Length L Ch R = 1 ,3020.7  ,530.4,532.2,536.9
BEGIN DESCRIPTION:
Cross Section 3020.7
END DESCRIPTION:
XS GIS Cut Line= 3
      3171380.68     13861741.78      3171091.63     13861937.59
      3170978.92     13862083.24
#Sta/Elev= 25
  4744.7    34.3  4844.7    32.4  4854.7    31.7  4864.7    28.3  4874.7    26.2
  4884.7    26.2  4894.7    22.6  4905.2   17.48  4920.8   11.63    4981   10.09
  4990.9       6  4994.6    5.24  4999.5    4.95  5009.1    5.53  5011.1    8.25
  5014.7   10.01  5020.8   12.83  5056.5   32.13  5078.3   31.97    5118    33.6
    5138    34.8    5168    34.1    5218    35.6    5238    35.2    5278    36.3
#Mann= 3 , 1 , 0
  4744.7     .14       0    4981     .05       0  5014.7     .14       0
Bank Sta=4981,5014.7
XS Rating Curve= 0
Exp/Cntr=.3,.1

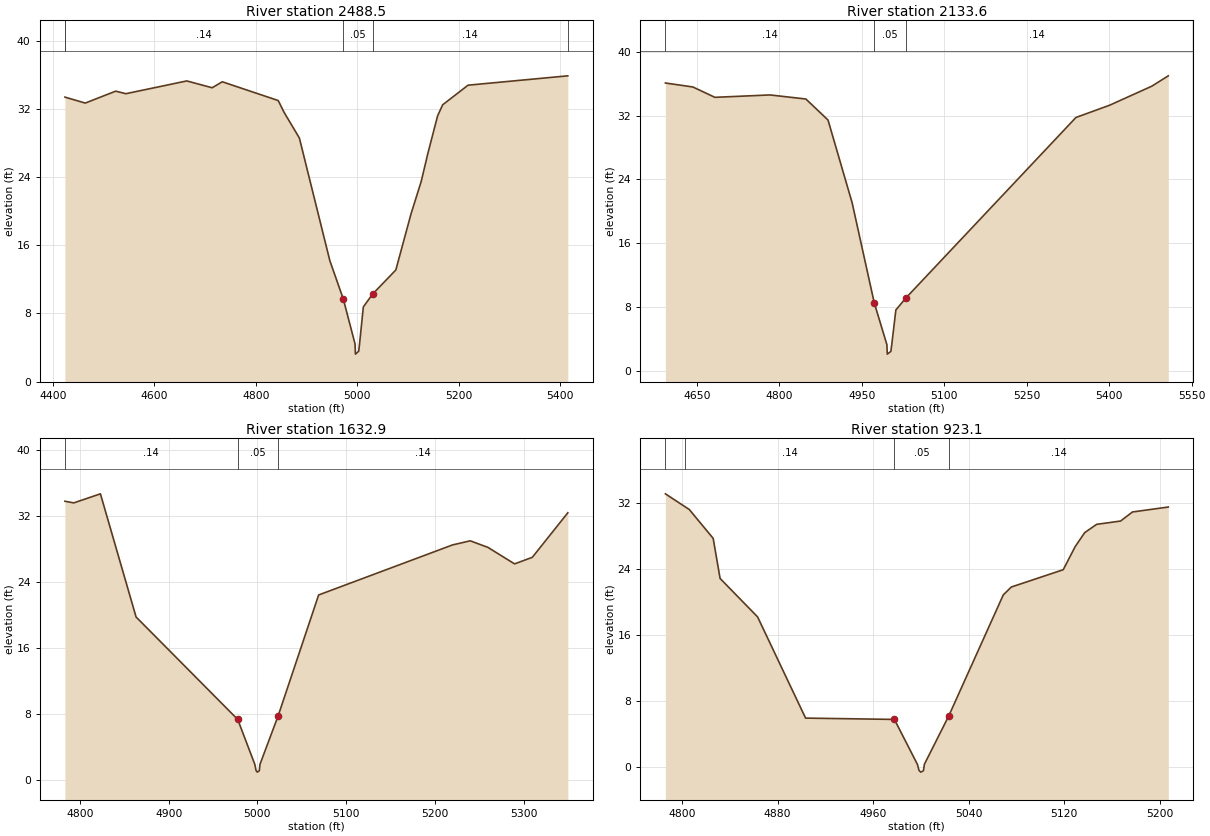
Type RM Length L Ch R = 1 ,2488.5  ,247.6,354.9,408.1
BEGIN DESCRIPTION:
Cross Section 2488.5-Interpolated
END DESCRIPTION:
XS GIS Cut Line= 4
      3171161.14     13861567.25      3170780.06      13861748.1
      3170573.38     13861954.78      3170405.44     13862174.39
#Sta/Elev= 28
  4424.1    33.4  4464.1    32.7  4524.1    34.1  4544.1    33.8  4664.1    35.3
  4714.1    34.5  4734.1    35.2  4844.1      33  4845.9    32.8  4855.9    31.6
  4885.9    28.6  4945.9    14.2  4972.6    9.66  4995.6    4.41  4996.3    3.22
  5002.8    3.56  5004.4    4.39  5011.9    8.76    5030   10.26  5075.9    13.1
  5105.9    19.7  5125.9    23.5  5135.9      26  5138.2    26.6  5158.2    31.2
  5168.2    32.5  5218.2    34.8  5414.7    35.9
#Mann= 5 , 1 , 0
  4424.1      .2       0  4424.1     .14       0  4972.6     .05       0
    5030     .14       0  5414.7      .2       0
Bank Sta=4972.6,5030
XS Rating Curve= 0
Exp/Cntr=.3,.1

Type RM Length L Ch R = 1 ,2133.6  ,536.1,500.7,417.5
BEGIN DESCRIPTION:
Cross Section 2133.6
END DESCRIPTION:
XS GIS Cut Line= 5
      3171068.55     13861549.67       3170900.1     13861614.29
      3170648.62     13861584.11       3170448.6     13861591.34
        3170168.     13861605.37
#Sta/Elev= 18
  4592.7    36.1  4642.7    35.6  4682.7    34.3  4782.9    34.6  4848.2   34.09
  4888.5   31.45  4932.4   21.05  4972.6     8.5  4995.6    3.25  4996.3    2.06
  5002.8     2.4  5004.4    3.23  5011.9     7.6    5030     9.1  5339.5   31.77
  5400.8   33.31  5477.5    35.7  5507.5      37
#Mann= 3 , 1 , 0
  4592.7     .14       0  4972.6     .05       0    5030     .14       0
Bank Sta=4972.6,5030
XS Rating Curve= 0
Exp/Cntr=.3,.1

Type RM Length L Ch R = 1 ,1632.9  ,957.5,709.8,513.7
BEGIN DESCRIPTION:
Cross Section 1632.9-Interpolated
END DESCRIPTION:
XS GIS Cut Line= 3
      3170802.55     13861092.15       3170459.7     13861186.16
      3170280.44      13861298.2
#Sta/Elev= 18
    4783    33.8    4793    33.6    4823    34.7  4863.2   19.76  4977.8    7.33
  4997.1    1.87  4998.4    1.15  4999.8     .94  5002.1     1.1  5002.9    1.89
  5023.4    7.78    5069   22.43  5219.9    28.5  5239.9      29  5259.9    28.2
  5289.9    26.2  5309.9      27  5349.9    32.4
#Mann= 3 , 1 , 0
    4783     .14       0  4977.8     .05       0  5023.4     .14       0
Bank Sta=4977.8,5023.4
XS Rating Curve= 0
Exp/Cntr=.3,.1

Type RM Length L Ch R = 1 ,923.1   ,0,0,0
BEGIN DESCRIPTION:
Cross Section  923.1
END DESCRIPTION:
XS GIS Cut Line= 4
      3170184.06     13860740.23      3170125.35     13860806.76
      3170079.84     13860995.82      3170056.21     13861131.79
#Sta/Elev= 23
    4786    33.1  4802.5   31.53    4806    31.2    4826    27.7  4831.8   22.84
  4863.2   18.18  4903.4    5.91  4977.8    5.75  4997.1     .29  4998.4    -.43
  4999.8    -.64  5002.1    -.48  5002.9     .31  5023.4     6.2    5069   20.85
  5075.7    21.8  5119.2    23.9  5129.2    26.7  5137.2    28.4  5147.2    29.4
  5167.2    29.8  5177.2    30.9  5207.2    31.5
#Mann= 4 , 1 , 0
    4786      .1       0  4802.5     .14       0  4977.8     .05       0
  5023.4     .14       0
Bank Sta=4977.8,5023.4
XS Rating Curve= 0
Exp/Cntr=.3,.1

Chan Stop Cuts=-1